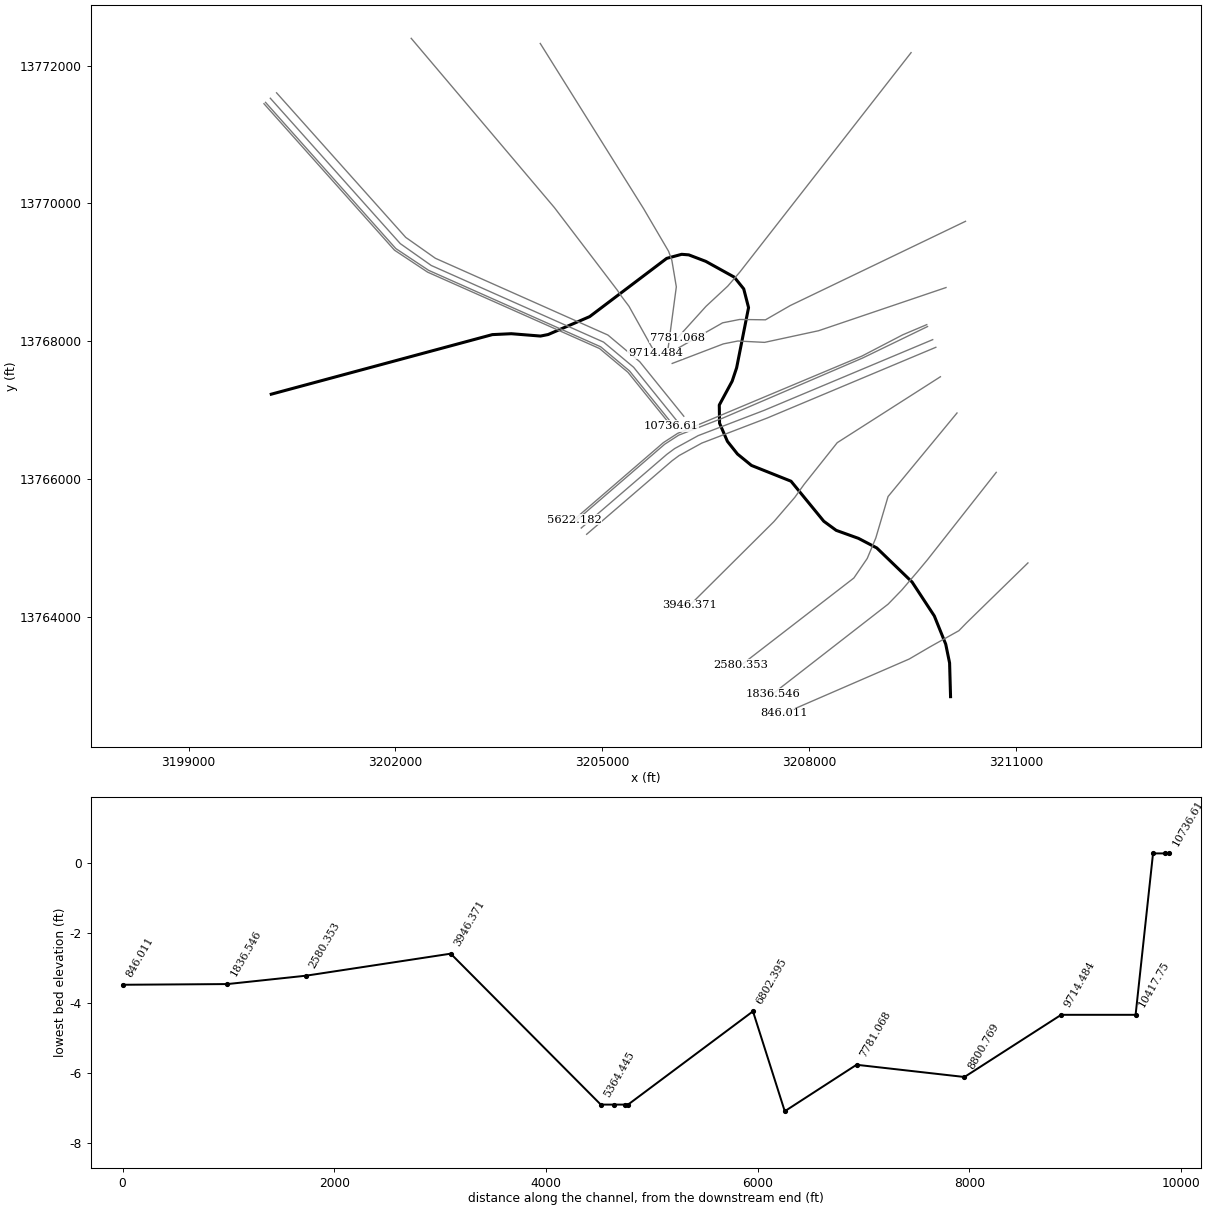
--- A107_00_00.prj (project) ---

Proj Title=A107-00-00
Current Plan=p01
Default Exp/Contr=.3,.1
English Units
Geom File=g01
Geom File=g02
Flow File=f01
Flow File=f02
Plan File=p01
Plan File=p02
Y Axis Title=Elevation
X Axis Title(PF)=Main Channel Distance
X Axis Title(XS)=Station
BEGIN DESCRIPTION:
Clear Creek Basin
Cow Bayou
A107-00-00
Flood Hazard Model
10, 2, 1 & 0.2% Events
Filename: A107_00_00.prj
Prepared by: Perry Vaught	Date: 2-02-04
Reviewed by: __________	Date:
Status: (FINAL)
END DESCRIPTION:
DSS Export Rating Curves= 0
DSS Export Rating Curve Sorted= 0
DSS Export Volume Flow Curves= 0
DXF OffsetX= 0
DXF OffsetY= 0
DXF ScaleX= 1
DXF ScaleY= 10

--- A107_00_00.p01 (plan) ---

Plan Title=FEMA Effective June 2007
Version=Version 3.0.1  Mar 2001
Short Identifier=FEMAeff0607
Geom File=g01
Flow File=f01
Subcritical Flow
K Sum by GR= 0
Std Step Tol= 0.003
Critical Tol= 0.003
Num of Std Step Trials= 20
Max Error Tol= 0.1
Flow Tol Ratio= 0.001
Split Flow NTrial= 30
Split Flow Tol= 0.02
Split Flow Ratio= 0.02
Log Output Level= 0
Friction Slope Method= 0
Unsteady Friction Slope Method= 2
Secant Critical Depth
Global Vel Dist= 0 , 0 , 0
Global Log Level= 0
CheckData=True
Encroach Param=-1 ,0,0, 2
Computation Interval=1HOUR
Output Interval=1HOUR
Run HTab= 0
Run UNet= 0
Run PostProcess= 0
UNET Theta= 1
UNET ZTol= 0.02
UNET ZSATol= 0.1
UNET MxIter= 20
UNET MaxInSteps= 20
UNET DtIC= 0
UNET DtMin= 0
UNET MaxCRTS= 20
UNET WFStab= 2
UNET SFStab= 1
UNET WFX= 1
UNET SFX= 1
UNET Convert EG Bridges=-1
UNET Use Existing IB Tables=-1
Instantaneous Interval=1HOUR
Write IC File= 0
Write Velocity= 0
Write Detailed= 0

--- A107_00_00.p02 (plan) ---

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Plan Title=Floodway
Short Identifier=Floodway0607
Geom File=g02
Flow File=f02
Encroach River=A107-00-00
Encroach Reach=A107-00-00_0008
Encroach Node=10736.61
       1    4931    5138
Encroach Node=10694.39
       1 4938.55 5061.45
Encroach Node=10638.47
       1 4938.55 5061.45
Encroach Node=10582.55
       1    4908 5061.45
Encroach Node=10417.75
       1 4889.29    5142
Encroach Node=9714.484
       1    4885 5119.98
Encroach Node=8800.769
       1 4892.47 5106.42
Encroach Node=7781.068
       1    4902 5092.86
Encroach Node=7102.868
       1 4931.72 5088.28
Encroach Node=6802.395
       1  4925.2  5094.8
Encroach Node=5622.182
       1    4913 5096.11
Encroach Node=5591.475
       1 4903.89 5096.11
Encroach Node=5538.32
       1 4903.89 5096.11
Encroach Node=5485.155
       1 4903.89 5096.11
Encroach Node=5364.445
       1 4903.89 5096.11
Encroach Node=3946.371
       1 4887.93 5117.91
Encroach Node=2580.353
       1 4861.12 5138.88
Encroach Node=1836.546
       1 4851.91 5148.09
Encroach Node=846.011
       1 4751.02 5248.98

--- A107_00_00.f01 (steady flow) ---

Flow Title=FEMA Effective June 2007
Version=Version 3.0.1  Mar 2001
Number of Profiles= 4
Profile Names=10PCT_10yr, 2PCT_50yr, 1PCT_100yr, 0.2PCT_500yr
River Rch & RM=Cow Bayou,Main            ,10736.61
    1309    1872    2168    2999
River Rch & RM=Cow Bayou,Main            ,10417.75
    1355    1940    2248    3113
River Rch & RM=Cow Bayou,Main            ,9714.484
    1417    2032    2356    3268
River Rch & RM=Cow Bayou,Main            ,8800.769
    1490    2139    2482    3450
River Rch & RM=Cow Bayou,Main            ,7781.068
    1540    2214    2570    3577
River Rch & RM=Cow Bayou,Main            ,7102.868
    1563    2247    2610    3634
River Rch & RM=Cow Bayou,Main            ,6802.395
    1655    2385    2773    3870
River Rch & RM=Cow Bayou,Main            ,5622.182
    1676    2417    2810    3923
River Rch & RM=Cow Bayou,Main            ,5364.445
    1797    2596    3021    4230
River Rch & RM=Cow Bayou,Main            ,3946.371
    1921    2781    3241    4549
River Rch & RM=Cow Bayou,Main            ,2580.353
    1992    2888    3367    4732
River Rch & RM=Cow Bayou,Main            ,1836.546
    2091    3036    3542    4988
River Rch & RM=Cow Bayou,A107-00-00      ,10736.61
    1309    1872    2168    2999
River Rch & RM=Cow Bayou,A107-00-00      ,10417.75
    1355    1940    2248    3113
River Rch & RM=Cow Bayou,A107-00-00      ,9714.484
    1417    2032    2356    3268
River Rch & RM=Cow Bayou,A107-00-00      ,8800.769
    1490    2139    2482    3450
River Rch & RM=Cow Bayou,A107-00-00      ,7781.068
    1540    2214    2570    3577
River Rch & RM=Cow Bayou,A107-00-00      ,7102.868
    1563    2247    2610    3634
River Rch & RM=Cow Bayou,A107-00-00      ,6802.395
    1655    2385    2773    3870
River Rch & RM=Cow Bayou,A107-00-00      ,5622.182
    1676    2417    2810    3923
River Rch & RM=Cow Bayou,A107-00-00      ,5364.445
    1797    2596    3021    4230
River Rch & RM=Cow Bayou,A107-00-00      ,3946.371
    1921    2781    3241    4549
River Rch & RM=Cow Bayou,A107-00-00      ,2580.353
    1992    2888    3367    4732
River Rch & RM=Cow Bayou,A107-00-00      ,1836.546
    2091    3036    3542    4988
River Rch & RM=A107-00-00,A107-00-00_0008            ,10736.61
    1309    1872    2168    2999
River Rch & RM=A107-00-00,A107-00-00_0008            ,10417.75
    1355    1940    2248    3113
River Rch & RM=A107-00-00,A107-00-00_0008            ,9714.484
    1417    2032    2356    3268
River Rch & RM=A107-00-00,A107-00-00_0008            ,8800.769
    1490    2139    2482    3450
River Rch & RM=A107-00-00,A107-00-00_0008            ,7781.068
    1540    2214    2570    3577
River Rch & RM=A107-00-00,A107-00-00_0008            ,7102.868
    1563    2247    2610    3634
River Rch & RM=A107-00-00,A107-00-00_0008            ,6802.395
    1655    2385    2773    3870
River Rch & RM=A107-00-00,A107-00-00_0008            ,5622.182
    1676    2417    2810    3923
River Rch & RM=A107-00-00,A107-00-00_0008            ,5364.445
    1797    2596    3021    4230
River Rch & RM=A107-00-00,A107-00-00_0008            ,3946.371
    1921    2781    3241    4549
River Rch & RM=A107-00-00,A107-00-00_0008            ,2580.353
    1992    2888    3367    4732
River Rch & RM=A107-00-00,A107-00-00_0008            ,1836.546
    2091    3036    3542    4988
Boundary for River Rch & Prof#=A107-00-00,A107-00-00_0008      , 1
Up Type= 0
Dn Type= 3
Dn Slope=.0002
DSS Import GetInterval= 0
DSS Import GetPeak= 0
DSS Import FillOption= 0

--- A107_00_00.f02 (steady flow) ---

Flow Title=Floodway
Version=Version 3.0.1  Mar 2001
Number of Profiles= 2
Profile Names=1PCT_100yr, 1PCTFloodway_100yrFW
River Rch & RM=A107-00-00,A107-00-00_0008      ,10736.61
    2168    2168
River Rch & RM=A107-00-00,A107-00-00_0008      ,10417.75
    2248    2248
River Rch & RM=A107-00-00,A107-00-00_0008      ,9714.484
    2356    2356
River Rch & RM=A107-00-00,A107-00-00_0008      ,8800.769
    2482    2482
River Rch & RM=A107-00-00,A107-00-00_0008      ,7781.068
    2570    2570
River Rch & RM=A107-00-00,A107-00-00_0008      ,7102.868
    2610    2610
River Rch & RM=A107-00-00,A107-00-00_0008      ,6802.395
    2773    2773
River Rch & RM=A107-00-00,A107-00-00_0008      ,5622.182
    2810    2810
River Rch & RM=A107-00-00,A107-00-00_0008      ,5364.445
    3021    3021
River Rch & RM=A107-00-00,A107-00-00_0008      ,3946.371
    3241    3241
River Rch & RM=A107-00-00,A107-00-00_0008      ,2580.353
    3367    3367
River Rch & RM=A107-00-00,A107-00-00_0008      ,1836.546
    3542    3542
Boundary for River Rch & Prof#=A107-00-00,A107-00-00_0008      , 1
Up Type= 0
Dn Type= 3
Dn Slope=.0002
DSS Import GetInterval= 0
DSS Import GetPeak= 0
DSS Import FillOption= 0

--- A107_00_00.g01 (geometry) ---

Geom Title=A107-00-00 June 2007
Version=Version 3.0.1  Mar 2001

River Reach=A107-00-00       ,A107-00-00_0008
Reach XY= 30
     3200198.343    13767232.468       3203406.5    13768097.001
        3203681.       13768110.        3204105.    13768075.999
      3204215.25       13768098.      3204818.25       13768358.
      3205935.75       13769203.      3206152.75       13769262.
        3206256.       13769254.       3206502.5       13769160.
      3206916.25       13768931.       3207053.5       13768760.
       3207123.5    13768489.001       3206950.5       13767616.
       3206885.5    13767420.999      3206698.75       13767075.
      3206702.75       13766811.      3206816.75    13766547.999
        3206963.    13766363.999       3207165.5       13766199.
       3207739.5       13765970.        3208215.    13765388.999
        3208395.    13765257.001      3208717.75    13765140.999
      3208983.75       13765002.      3209496.25       13764507.
      3209818.75       13764015.        3209984.       13763606.
      3210040.25    13763332.999      3210054.25    13762843.999

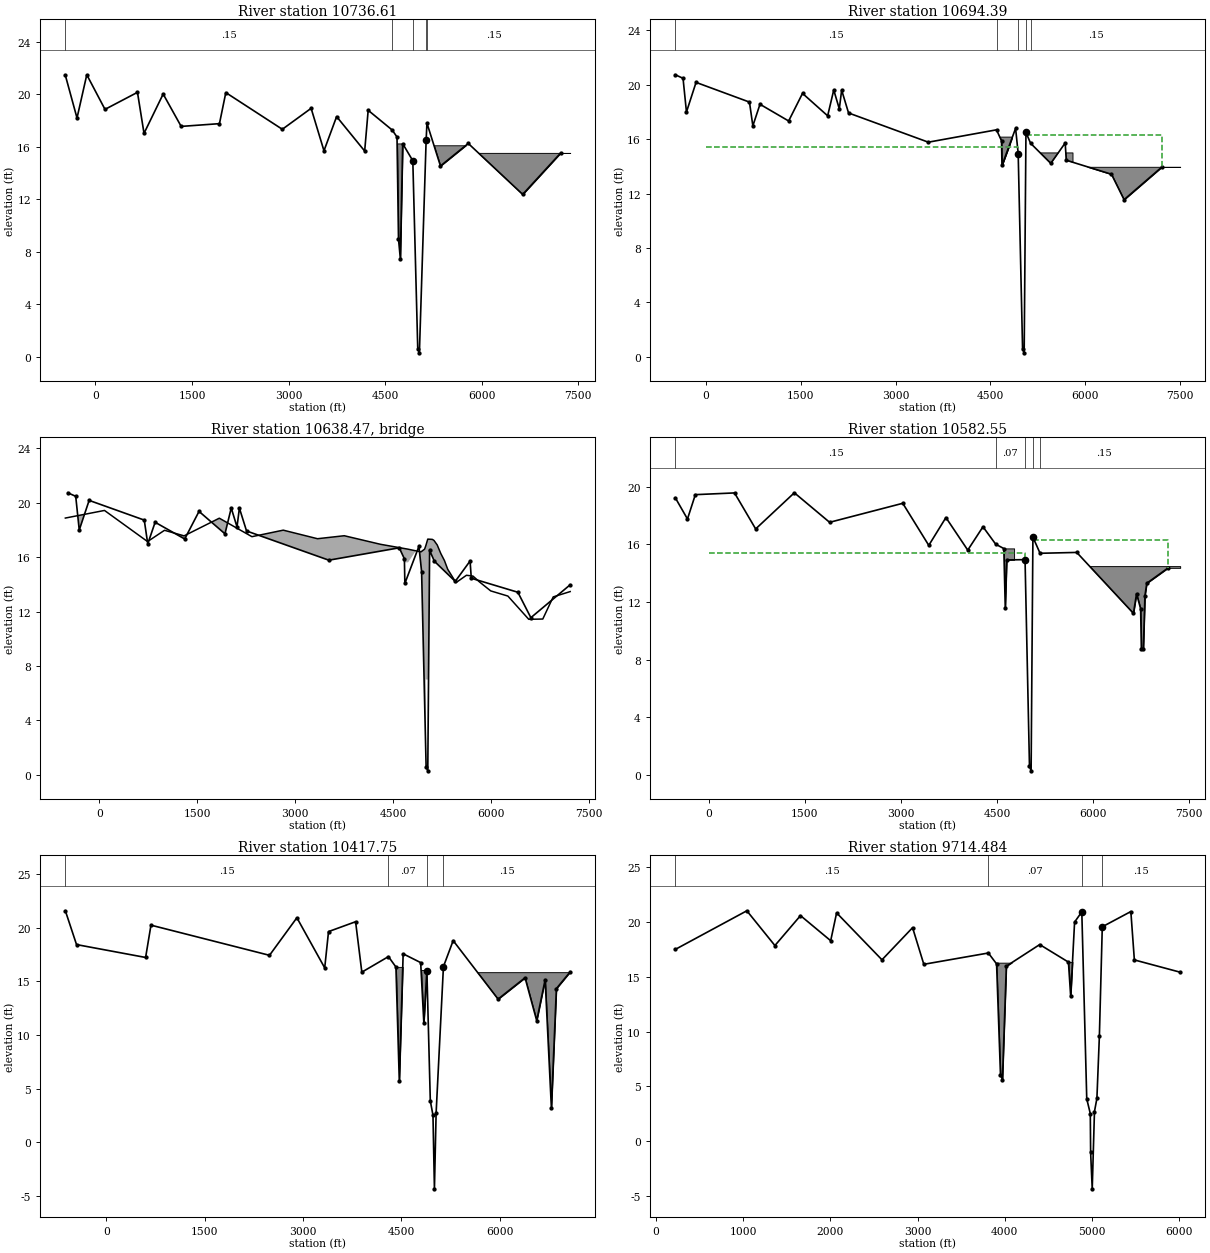
Type RM Length L Ch R = 1 ,10736.61,39.11,42.22,41.7
XS GIS Cut Line= 6
     3200092.673    13771446.804     3201986.133    13769322.236
     3202466.939    13769003.273     3204961.999    13767894.751
     3205373.816    13767549.904     3206003.254    13766770.799
#Sta/Elev= 30
 -468.47   21.46 -287.21    18.2 -135.35    21.5  147.69   18.86  652.35   20.16
  754.07   17.03 1051.57   20.03 1331.43   17.56 1926.28   17.77 2025.11   20.14
 2903.31   17.34 3350.86   18.94 3550.53    15.7 3746.95   18.31 4182.94   15.68
 4237.37   18.79 4611.33   17.28 4685.43   16.75 4708.46    8.97 4737.15    7.47
  4774.1   16.24    4931   14.94 5007.76     .59 5033.19     .28    5138    16.5
 5150.54   17.81 5360.59   14.54 5792.88   16.26 6638.14   12.37 7228.18   15.53
#Mann= 5 ,-1 , 0
 -468.47     .15       0 4611.33     .07       0    4931    .015       0
    5138     .07       0 5150.54     .15       0
#Block Obstruct= 3 ,-1
 4606.74  4791.3   16.26 5195.14 5806.46   16.12 5806.46 7376.44   15.54
Bank Sta=4931,5138
XS Rating Curve= 0
Exp/Cntr=.5,.3

Type RM Length L Ch R = 1 ,10694.39,104.29,111.84,109.83
BEGIN DESCRIPTION:
El Camino Real
END DESCRIPTION:
XS GIS Cut Line= 6
     3200115.347    13771466.451     3202005.468    13769345.367
     3202481.534    13769029.562     3204977.789    13767920.294
     3205396.099    13767570.002      3206026.84    13766789.337
#Sta/Elev= 30
 -484.87   20.74    -363   20.48 -308.91      18 -157.26   20.18  687.64   18.73
  741.25   16.98  854.05   18.57 1307.52   17.34 1526.98   19.37 1924.57   17.72
 2020.87   19.62 2109.04   18.23 2145.96   19.61 2255.28   17.93 3516.73   15.78
 4595.86   16.69 4674.86   15.88 4681.96   14.07 4897.55    16.8 4938.55   14.94
 5007.76     .59 5033.19     .28 5061.45    16.5 5134.72    15.7 5454.38   14.22
 5681.67   15.72 5700.34   14.45 6414.23   13.42 6613.35   11.55  7213.2   13.96
#Mann= 5 ,-1 , 0
 -484.87     .15       0 4595.86     .07       0 4938.55    .015       0
 5061.45     .07       0 5134.72     .15       0
#XS Ineff= 2 , 0
       0 4938.55   15.43 5061.45       0   16.32
Permanent Ineff=
       F       F
#Block Obstruct= 4 ,-1
 4605.83  4806.1   15.91 4628.98 4840.88   16.19 5126.68 5805.59   14.99
 5663.67 7500.95   13.97
Bank Sta=4938.55,5061.45
XS Rating Curve= 0
Exp/Cntr=.5,.3

Type RM Length L Ch R = 3 ,10638.47,,,
Node Photo=K:\Projects\C2001-041 Harris County FEMA\4-Clear Creek Basin\Cow Bayou\Survey info\Photos\215s-cowbayou1p1.jpg
BEGIN DESCRIPTION:
El Camino Real
END DESCRIPTION:
Bridge Culvert--1,0,-1,-1, 0
Deck Dist Width WeirC Skew NumUp NumDn MinLoCord MaxHiCord MaxSubmerge Is_Ogee
9,93,2.6,0, 36, 36, , , .95, 0, 0,0,,
    -522      78     738     998    1298    1838    2338    2818    3018    3343
    3753    4308    4731    4928    4984 5002.03 5002.03    5033 5038.92 5038.92
    5104    5129    5178    5233    5289    5339    5466    5626    5726    5826
    5998    6261    6581    6796    6956    7216
   18.88   19.44   17.15   17.98   17.57   18.87   17.51   17.99   17.75   17.36
   17.58   16.95   16.59   16.39   16.59   16.83   16.83   17.33   17.33   17.33
   17.31   17.23    16.9   16.27   15.75   15.11   14.13   14.67   14.61   14.18
   13.52   13.14   11.43   11.45   13.08   13.47
   14.67   14.67   14.67   14.67   14.67   14.67   14.67   14.67   14.67   14.67
   15.62   15.62   15.62   14.67       0       0       7       7       7       0
   14.67   14.67   14.67   14.67   14.67       0       0       0       0       0
       0       0    10.2    10.2    10.2    10.2
    -522      78     738     998    1298    1838    2338    2818    3018    3343
    3753    4308    4731    4928    4984 5002.03 5002.03    5033 5038.92 5038.92
    5104    5129    5178    5233    5289    5339    5466    5626    5726    5826
    5998    6261    6581    6796    6956    7216
   18.88   19.44   17.15   17.98   17.57   18.87   17.51   17.99   17.75   17.36
   17.58   16.95   16.59   16.39   16.59   16.83   16.83   17.33   17.33   17.33
   17.31   17.23    16.9   16.27   15.75   15.11   14.13   14.67   14.61   14.18
   13.52   13.14   11.43   11.45   13.08   13.47
   14.67   14.67   14.67   14.67   14.67   14.67   14.67   14.67   14.67   14.67
   15.62   15.62   15.62   14.67       0       0       7       7       7       0
   14.67   14.67   14.67   14.67   14.67       0       0       0       0       0
       0       0    10.2    10.2    10.2    10.2
BR Coef=-1 , 1 , 0 ,, 0 ,,,.8,-1,2,0,
WSPro=,,,, 1 ,,,, 0 ,,,, 0 ,,,,-1 ,-1 ,-1 , 0 , 0 , 0 , 0 , 0
BC Design=,, 0 ,, 0 ,,,,,,

Type RM Length L Ch R = 1 ,10582.55,156.43,164.79,159.6
BEGIN DESCRIPTION:
El Camino Real
END DESCRIPTION:
XS GIS Cut Line= 6
     3200184.761    13771526.442     3202070.383    13769416.952
     3202520.454    13769099.665     3205019.897    13767988.406
     3205455.522    13767623.596     3206089.738    13766838.774
#Sta/Elev= 30
 -522.68   19.23 -333.29   17.76 -210.38   19.45  401.66   19.57  731.73   17.07
  1335.7   19.58 1886.47   17.53 3028.84   18.85 3435.15   15.93 3702.81   17.86
 4043.84    15.6 4281.57   17.22 4480.44   16.01 4607.14   15.71 4629.57    11.6
  4652.3   14.92 4938.55   14.94 5007.76     .59 5033.19     .28 5061.45    16.5
 5173.18   15.38 5745.95   15.44  6631.1   11.21 6679.78   12.57 6743.55   11.53
 6755.21    8.71 6786.28    8.76 6811.11   12.44 6839.69    13.3 7174.43   14.37
#Mann= 5 ,-1 , 0
 -522.68     .15       0 4480.44     .07       0 4938.55    .015       0
 5061.45     .07       0 5173.18     .15       0
#XS Ineff= 2 , 0
       0 4938.55   15.42 5061.45       0   16.32
Permanent Ineff=
       F       F
#Block Obstruct= 2 ,-1
  4562.5 4767.29   15.72 5713.34 7361.08   14.49
Bank Sta=4938.55,5061.45
XS Rating Curve= 0
Exp/Cntr=.5,.3

Type RM Length L Ch R = 1 ,10417.75,894.9,703.27,554.08
XS GIS Cut Line= 6
     3200275.281    13771605.224     3202149.131    13769507.911
     3202579.531    13769204.492      3205083.06    13768090.576
     3205544.655    13767703.987     3206184.084    13766912.928
#Sta/Elev= 30
 -627.11   21.57 -456.45   18.42  597.59   17.22  679.38   20.23 2487.97   17.42
 2905.89   20.92 3330.46   16.25 3388.53   19.63 3801.69   20.55  3896.9   15.85
 4302.87    17.3 4417.12   16.33 4468.63     5.7 4527.41   17.56 4794.83   16.74
 4843.04   11.12 4889.29      16 4941.77    3.86 4982.37    2.52  5004.6   -4.34
 5030.27    2.71    5142   16.37 5290.53   18.79 5975.46   13.34  6387.4   15.33
 6565.23   11.33 6693.84   15.15 6789.23    3.21 6865.55   14.32 7075.98   15.88
#Mann= 4 ,-1 , 0
 -627.11     .15       0 4302.87     .07       0 4889.29    .035       0
    5142     .15       0
#Block Obstruct= 3 ,-1
  4395.9 4573.88   16.34  4781.8 4884.42   16.05 5617.49 7271.11   15.85
Bank Sta=4889.29,5142
XS Rating Curve= 0
Exp/Cntr=.3,.1

Type RM Length L Ch R = 1 ,9714.484,946.23,913.72,784.96
XS GIS Cut Line= 6
     3202228.957    13772395.564     3204307.211    13769938.989
     3205218.472    13768742.628     3205278.271    13768654.595
     3205388.576    13768508.201     3205769.128    13767826.172
#Sta/Elev= 30
   221.3   17.49 1041.67   21.01 1363.71   17.84 1657.33   20.57 2003.78   18.28
 2071.68   20.82  2592.2   16.54  2943.3   19.47 3072.38   16.13 3812.57   17.16
 3907.13   16.17 3951.95    6.06 3974.37    5.62 4019.19   15.96 4402.13   17.93
  4731.6   16.33  4757.4   13.22 4802.25   19.98    4885   20.91 4941.77    3.86
 4982.37    2.52  4986.2   -1.02  5004.6   -4.34 5030.27    2.71 5058.23     3.9
  5086.7    9.59 5119.98   19.55 5447.71   20.94    5488   16.53 6013.67   15.41
#Mann= 4 ,-1 , 0
   221.3     .15       0 3812.57     .07       0    4885    .035       0
 5119.98     .15       0
#Block Obstruct= 2 ,-1
 3854.59 4163.29   16.28 4697.61 4806.14   16.34
Bank Sta=4885,5119.98
XS Rating Curve= 0
Exp/Cntr=.3,.1

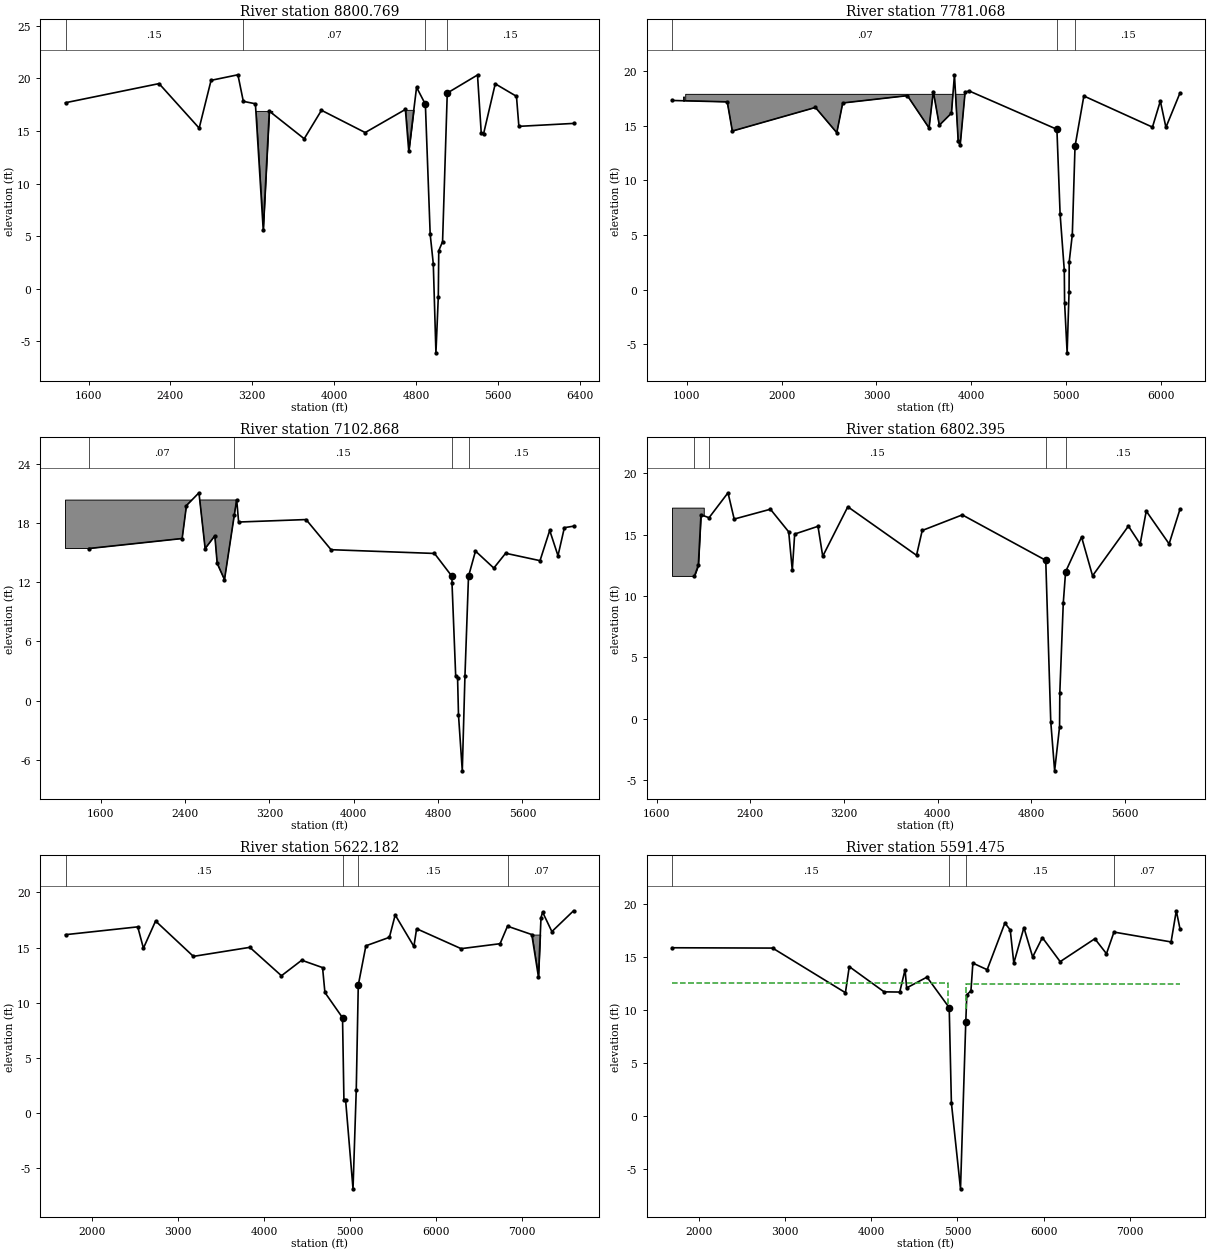
Type RM Length L Ch R = 1 ,8800.769,1277.48,1019.7,753.64
XS GIS Cut Line= 6
     3204101.246    13772321.152     3205600.976    13769923.766
     3205962.954    13769306.159     3206010.748    13769174.323
     3206075.547    13768789.908     3205956.933    13767905.248
#Sta/Elev= 30
 1374.19   17.69 2288.74   19.51 2680.99   15.27 2797.26   19.82 3059.74   20.35
 3112.59   17.82 3230.71   17.59 3307.09    5.61 3366.71   16.89 3707.93   14.26
 3876.62   16.97 4303.95   14.85  4697.1   17.05 4730.17   13.07 4806.31   19.16
 4892.47   17.54 4939.47    5.17 4969.83    2.36 4995.68   -6.12 5018.82    -.79
 5023.38     3.6 5060.53    4.47 5106.42   18.61 5402.12   20.33 5438.36   14.84
 5461.64   14.74 5575.51   19.49 5782.99    18.3 5806.61   15.44 6341.06   15.72
#Mann= 4 ,-1 , 0
 1374.19     .15       0 3112.59     .07       0 4892.47    .035       0
 5106.42     .15       0
#Block Obstruct= 2 ,-1
 3038.14 3395.71   16.91 4695.09 4786.66   17.01
Bank Sta=4892.47,5106.42
XS Rating Curve= 0
Exp/Cntr=.3,.1

Type RM Length L Ch R = 1 ,7781.068,888.8,678.2,480.68
XS GIS Cut Line= 6
     3209481.515    13772187.976     3207128.709    13769173.444
     3206996.514    13769003.958     3206821.881    13768800.727
     3206506.803    13768507.895     3206092.198    13768049.648
#Sta/Elev= 30
   844.5   17.32 1427.15   17.19  1480.7   14.52 2356.72   16.68 2581.85   14.37
  2644.5   17.09 3325.81   17.76 3554.38    14.8 3599.02   18.14 3662.34   15.05
  3790.5   16.16 3821.95   19.67  3861.4   13.61 3882.12    13.2 3934.31   18.08
  3976.8   18.19    4902   14.68 4935.62    6.93 4979.85    1.77 4982.93   -1.17
  5009.7   -5.77 5029.95    -.19 5031.71    2.57 5064.38    5.05 5092.86   13.12
 5185.94   17.73 5909.15   14.88 5992.21   17.27 6050.89   14.86 6199.53   18.01
#Mann= 3 ,-1 , 0
   844.5     .07       0    4902    .035       0 5092.86     .15       0
#Block Obstruct= 2 ,-1
  960.48   972.8   17.68  989.23 3954.48   17.88
Bank Sta=4902,5092.86
XS Rating Curve= 0
Exp/Cntr=.3,.1

Type RM Length L Ch R = 1 ,7102.868,340.06,300.47,331.07
XS GIS Cut Line= 6
     3210270.975    13769740.798     3207728.795    13768518.806
     3207368.744    13768311.503      3206994.34    13768316.806
     3206746.837    13768267.861     3206114.019    13767907.809
#Sta/Elev= 30
 1489.85    15.4 2373.07   16.41 2413.96   19.75 2532.43   21.04 2591.15   15.39
 2683.05   16.69  2705.4   13.89  2774.6   12.25 2868.18   18.83 2890.25   20.34
 2908.53   18.08 3548.07   18.33 3784.92   15.28 4765.67    14.9 4931.72   12.58
 4931.72   11.93 4966.88    2.46 4984.67    2.31 4993.35   -1.44 5029.31    -7.1
 5054.52    2.48 5088.28   12.58 5154.47   15.14 5328.22   13.42 5440.19   14.92
 5766.37   14.17 5858.35   17.23 5936.82   14.67 5997.27   17.51 6084.29   17.66
#Mann= 4 ,-1 , 0
 1489.85     .07       0 2868.18     .15       0 4931.72    .035       0
 5088.28     .15       0
#Block Obstruct= 2 ,-1
 1267.07  2569.2    20.3 2502.79  2890.5   20.31
Bank Sta=4931.72,5088.28
XS Rating Curve= 0
Exp/Cntr=.3,.1

Type RM Length L Ch R = 1 ,6802.395,1018.19,1180.21,1248.04
XS GIS Cut Line= 6
     3209988.264    13768779.727     3208139.409    13768153.384
     3207355.585    13767984.324     3206968.116    13768004.132
     3206757.748    13767962.363     3206015.824    13767678.686
#Sta/Elev= 30
 1921.91   11.63 1954.81    12.5 1977.37   16.61 2046.45   16.37 2208.54    18.4
 2261.28   16.26 2571.19   17.06 2727.41   15.22 2758.13   12.09 2778.54   15.04
 2977.96   15.67 3018.39   13.23 3232.78   17.26 3820.33   13.31 3868.98   15.33
 4211.68    16.6  4925.2    12.9 4967.94    -.23 5001.08   -4.24 5043.22    -.65
 5045.41    2.13  5074.8    9.39  5094.8   11.97 5231.31    14.8 5325.29   11.64
 5631.94   15.69 5732.33   14.23 5784.39   16.91 5979.85   14.24 6073.08   17.07
#Mann= 4 ,-1 , 0
 1921.91     .07       0 2046.45     .15       0  4925.2    .035       0
  5094.8     .15       0
#Block Obstruct= 1 ,-1
 1729.44 2001.19   17.19
Bank Sta=4925.2,5094.8
XS Rating Curve= 0
Exp/Cntr=.3,.1

Type RM Length L Ch R = 1 ,5622.182,34.3,30.71,30.01
XS GIS Cut Line= 6
     3209708.766    13768241.691     3209361.974    13768094.813
     3208768.718    13767785.919     3206095.749    13766664.552
     3205888.534    13766530.479     3204591.938    13765412.309
#Sta/Elev= 30
 1692.49   16.17 2532.24   16.88 2598.14   14.94 2739.68   17.41 3179.13    14.2
 3835.44   15.02 4202.97   12.44 4438.64   13.85 4680.86   13.18 4708.31   10.92
    4913    8.63 4929.21     1.2 4948.26     1.2    5035   -6.91 5072.67     2.1
 5096.11   11.59 5184.69   15.16 5457.92   15.93  5525.3   17.96 5742.74    15.1
 5774.35   16.71 6291.78    14.9 6744.49   15.35 6830.95   16.94 7113.41   16.18
 7190.38   12.35 7220.48   17.71 7238.79   18.22 7346.81   16.45 7598.76   18.34
#Mann= 4 ,-1 , 0
 1692.49     .15       0    4913    .035       0 5096.11     .15       0
 6830.95     .07       0
#Block Obstruct= 1 ,-1
  7112.8 7233.04   16.18
Bank Sta=4913,5096.11
XS Rating Curve= 0
Exp/Cntr=.5,.3

Type RM Length L Ch R = 1 ,5591.475,127.7,106.32,116.13
BEGIN DESCRIPTION:
NASA Rd 1
END DESCRIPTION:
XS GIS Cut Line= 6
     3209720.425    13768214.049     3208780.501    13767758.328
     3206745.123    13766883.754     3206110.975    13766638.672
     3205906.775    13766506.549     3204611.473    13765389.542
#Sta/Elev= 30
 1685.91   15.84 2854.29   15.81 3699.15    11.6 3743.83   14.06 4148.26   11.68
 4329.48   11.66 4391.57   13.77 4409.79   12.05 4645.98   13.07 4903.89   10.19
 4929.21     1.2    5035   -6.91 5096.11    8.84 5108.33    11.4 5156.11   11.78
 5178.58   14.39 5344.44   13.77 5550.03   18.17 5612.19   17.52 5653.75   14.39
 5770.81   17.74 5872.43   14.97 5985.08    16.8 6191.79   14.53 6594.17   16.69
 6729.24   15.28 6816.26   17.32 7479.37   16.39 7539.61   19.33 7582.87   17.62
#Mann= 4 ,-1 , 0
 1685.91     .15       0 4903.89    .035       0 5096.11     .15       0
 6816.26     .07       0
#XS Ineff= 2 , 0
       0    4892   12.51    5102       0   12.43
Permanent Ineff=
       F       F
Bank Sta=4903.89,5096.11
XS Rating Curve= 0
Exp/Cntr=.5,.3

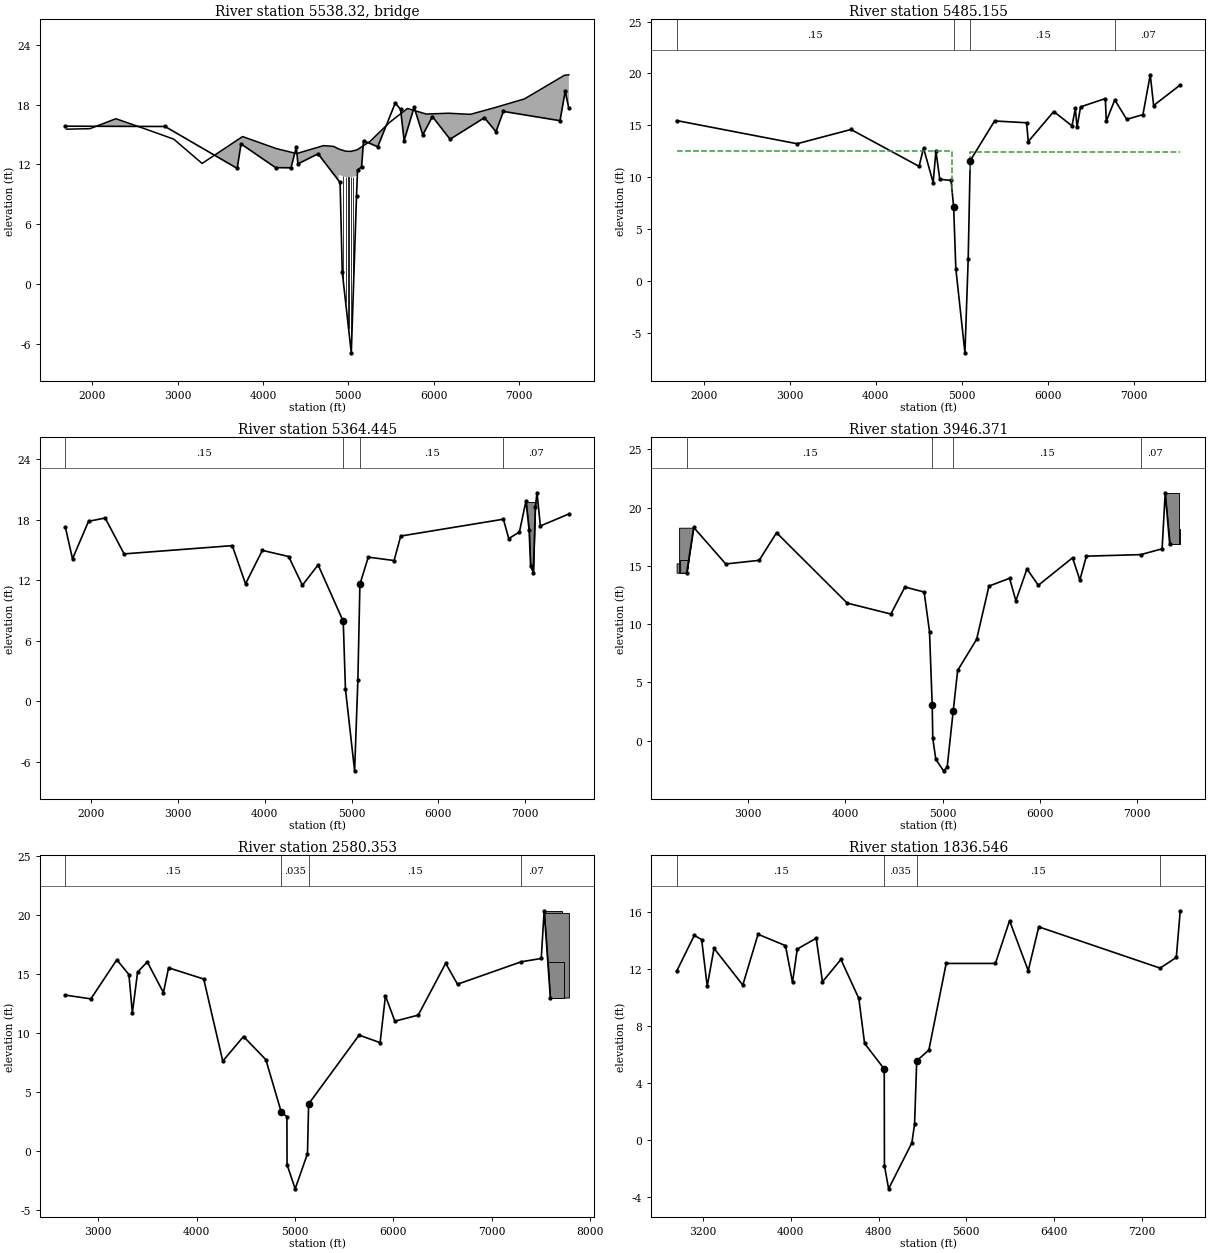
Type RM Length L Ch R = 3 ,5538.32 ,,,
Node Photo=K:\Projects\C2001-041 Harris County FEMA\4-Clear Creek Basin\Cow Bayou\Survey info\Photos\215s-cowbayou2p1.jpg
BEGIN DESCRIPTION:
NASA RD 1
END DESCRIPTION:
Bridge Culvert--1,0,-1,-1, 0
Deck Dist Width WeirC Skew NumUp NumDn MinLoCord MaxHiCord MaxSubmerge Is_Ogee
1,97,2.6,0, 26, 26, , , .95, 0, 0,0,,
    1700    1975    2278    2624    2956    3288    3762    4154    4394    4709
    4829    4888    4888    4969    5029    5102    5254    5482    5692    5912
    6172    6430    6706    7063    7531    7583
   15.54   15.59   16.59   15.56   14.54    12.1    14.8    13.6   13.09   13.89
   13.81   13.55   13.55   13.33   13.31   13.46   14.31   16.21   17.62   17.06
   17.14   17.03   17.68   18.58   20.95      21
                                                                                
                   10.95   10.73   10.71   10.86
                                                
    1700    1975    2278    2624    2956    3288    3762    4154    4394    4709
    4829    4888    4888    4969    5029    5102    5254    5482    5692    5912
    6172    6430    6706    7063    7531    7583
   15.54   15.59   16.59   15.56   14.54    12.1    14.8    13.6   13.09   13.89
   13.81   13.55   13.55   13.33   13.31   13.46   14.31   16.21   17.62   17.06
   17.14   17.03   17.68   18.58   20.95      21
                                                                                
                   10.95   10.73   10.71   10.86
                                                
Pier Skew, UpSta & Num, DnSta & Num=  ,4938, 4 ,4938, 4 , 3 , 3 , 0 ,,
     1.3     1.3     1.5     1.5
    1.11     9.3   9.301     111
     1.3     1.3     1.5     1.5
    1.11     9.3   9.301      11
Pier Skew, UpSta & Num, DnSta & Num=  ,4968, 4 ,4968, 4 , 3 , 3 , 0 ,,
     1.3     1.3     1.5     1.5
   -2.17    9.23   9.231      11
     1.3     1.3     1.5     1.5
   -2.17    9.23   9.231      11
Pier Skew, UpSta & Num, DnSta & Num=  ,5002, 4 ,5002, 4 , 3 , 3 , 0 ,,
     1.3     1.3     1.5     1.5
   -3.54    9.22    9.22      11
     1.3     1.3     1.5     1.5
   -3.54    9.22    9.22      11
Pier Skew, UpSta & Num, DnSta & Num=  ,5033, 4 ,5033, 4 , 3 , 3 , 0 ,,
     1.3     1.3     1.5     1.5
   -6.91    9.22    9.22      11
     1.3     1.3     1.5     1.5
   -6.91    9.22    9.22      11
Pier Skew, UpSta & Num, DnSta & Num=  ,5060, 4 ,5060, 4 , 3 , 3 , 0 ,,
     1.3     1.3     1.5     1.5
    -.82    9.27   9.271      11
     1.3     1.3     1.5     1.5
    -.82    9.27   9.271      11
BR Coef=-1 , 1 , 0 ,1.25, 0 ,,,.8,-1,2,0,
WSPro=,,,, 1 ,,,, 0 ,,,, 0 ,,,,-1 ,-1 ,-1 , 0 , 0 , 0 , 0 , 0
BC Design=,, 0 ,, 0 ,,,,,,

Type RM Length L Ch R = 1 ,5485.155,120.67,120.71,120.21
BEGIN DESCRIPTION:
NASA Rd 1
END DESCRIPTION:
XS GIS Cut Line= 6
     3209794.991    13768023.859     3207347.475    13766997.351
     3206392.984    13766631.429     3206050.732    13766443.232
     3205939.146    13766360.792      3204695.88    13765290.734
#Sta/Elev= 30
 1687.98   15.46 3085.95   13.23 3712.03    14.6 4502.48   11.05 4554.53   12.81
 4666.08    9.48 4698.15   12.52 4742.79    9.81    4874    9.69 4903.89    7.13
 4929.21     1.2    5035   -6.91 5072.67     2.1 5096.11   11.59 5378.48   15.42
 5750.42   15.25  5770.3   13.44 6065.87   16.33 6277.94   14.95 6317.06   16.64
 6335.76    14.8 6377.55   16.78  6665.1   17.58 6675.74   15.39  6774.4   17.45
 6912.97   15.58 7101.25   16.03 7186.49   19.87 7225.56   16.91 7534.44   18.89
#Mann= 4 ,-1 , 0
 1687.98     .15       0 4903.89    .035       0 5096.11     .15       0
  6774.4     .07       0
#XS Ineff= 2 , 0
       0    4888    12.5    5094       0    12.4
Permanent Ineff=
       F       F
Bank Sta=4903.89,5096.11
XS Rating Curve= 0
Exp/Cntr=.5,.3

Type RM Length L Ch R = 1 ,5364.445,1224.64,1418.07,1587.05
XS GIS Cut Line= 6
     3209840.681    13767912.898     3207393.437    13766886.462
     3206444.511    13766522.891     3206115.934    13766342.206
     3206014.575    13766267.321     3204774.472    13765200.051
#Sta/Elev= 30
 1698.38   17.28 1781.72   14.11 1966.33   17.83 2158.27   18.16 2376.48    14.6
 3624.27   15.42 3776.97   11.63 3970.93   14.95 4274.33   14.34 4432.58   11.49
 4614.13   13.51 4903.89    7.91 4929.21     1.2    5035   -6.91 5072.67     2.1
 5096.11   11.59 5192.39   14.28 5490.43   13.94 5566.49   16.37    6751   18.04
 6812.45   16.12  6935.4   16.77 7011.06   19.84 7047.18   16.98 7064.23    13.4
 7096.13   12.74 7119.16   19.28 7138.66   20.66 7177.18   17.37 7505.99   18.56
#Mann= 4 ,-1 , 0
 1698.38     .15       0 4903.89    .035       0 5096.11     .15       0
    6751     .07       0
#Block Obstruct= 1 ,-1
 7009.38 7142.61   19.74
Bank Sta=4903.89,5096.11
XS Rating Curve= 0
Exp/Cntr=.3,.1

Type RM Length L Ch R = 1 ,3946.371,1206.78,1366.02,1417.91
XS GIS Cut Line= 6
     3209906.848    13767485.458     3208410.302    13766529.129
     3207930.161    13765925.116      3207794.68    13765736.125
     3207490.474    13765382.994     3206271.338    13764171.158
#Sta/Elev= 30
 2368.35   14.42 2440.01   18.31 2769.66   15.17 3113.09   15.48 3291.78   17.85
 4018.09   11.81 4467.32   10.87 4611.55   13.19 4809.13   12.76 4864.44    9.36
 4892.12    3.04 4898.08     .21 4929.04    -1.6 5008.85   -2.59 5045.82   -2.29
 5107.88    2.54 5153.85    6.03 5348.79     8.7 5475.68   13.27 5687.64   13.94
 5752.27   12.01 5866.36   14.74 5983.03   13.34 6335.11    15.7 6410.51   13.79
 6476.94   15.84 7035.81   15.97 7255.83   16.47 7287.65   21.28 7333.74   16.85
#Mann= 4 ,-1 , 0
 2368.35     .15       0 4892.12    .035       0 5107.88     .15       0
 7035.81     .07       0
#Block Obstruct= 5 ,-1
  2264.6 2414.78   15.22 2289.93 2442.92   18.28 2300.36 2421.93   15.51
 7270.56 7442.19   18.21 7287.28 7430.39   21.24
Bank Sta=4892.12,5107.88
XS Rating Curve= 0
Exp/Cntr=.3,.1

Type RM Length L Ch R = 1 ,2580.353,1123.23,743.81,638.86
XS GIS Cut Line= 6
     3210147.755    13766959.842     3209147.625    13765748.005
     3208969.792    13765146.757     3208845.333    13764849.503
      3208651.21     13764565.37      3207015.96    13763302.432
#Sta/Elev= 30
 2665.28   13.19 2925.49   12.87 3189.09   16.18  3312.1   14.93 3347.15   11.68
 3400.43   15.14 3498.65      16 3662.76    13.4 3715.32    15.5 4072.48   14.55
 4266.06     7.6 4477.01    9.68 4704.15    7.72 4861.12    3.27 4918.24    2.89
 4919.46   -1.16 5001.82   -3.22 5127.28    -.25 5138.88    3.97 5652.02     9.8
 5865.51    9.16 5919.87   13.12 6015.67   10.98 6252.72   11.49 6532.12   15.88
 6652.38   14.11 7300.22   16.01 7503.56   16.29 7532.98   20.33 7596.06   12.98
#Mann= 4 ,-1 , 0
 2665.28     .15       0 4861.12    .035       0 5138.88     .15       0
 7300.22     .07       0
#Block Obstruct= 3 ,-1
 7532.77 7711.57   20.28 7535.13  7784.5   20.15 7556.62  7735.4   15.95
Bank Sta=4861.12,5138.88
XS Rating Curve= 0
Exp/Cntr=.3,.1

Type RM Length L Ch R = 1 ,1836.546,1090.62,990.53,841.94
XS GIS Cut Line= 6
     3210717.172    13766098.416     3209717.042    13764828.178
     3209566.968    13764648.354     3209347.044    13764391.297
     3209147.625    13764185.758     3207475.874    13762886.319
#Sta/Elev= 30
 2958.42   11.83 3119.33   14.35 3186.42   14.06 3237.38   10.78 3299.42   13.44
 3561.89   10.86 3700.89   14.43 3950.91   13.63 4015.35   11.05 4058.53   13.39
 4231.24   14.15 4288.51   11.09 4456.57   12.66 4620.12    9.92 4672.62    6.76
 4851.91    4.96 4853.64   -1.82 4891.69   -3.46 5103.75    -.23 5128.49    1.09
 5148.09    5.54  5258.7    6.29 5416.85   12.38  5865.7   12.38 5994.95   15.38
 6164.99   11.87  6261.2   14.95 7367.69   12.05 7515.47    12.8 7551.41   16.08
#Mann= 4 ,-1 , 0
 2958.42     .15       0 4851.91    .035       0 5148.09     .15       0
 7367.69     .07       0
Bank Sta=4851.91,5148.09
XS Rating Curve= 0
Exp/Cntr=.3,.1

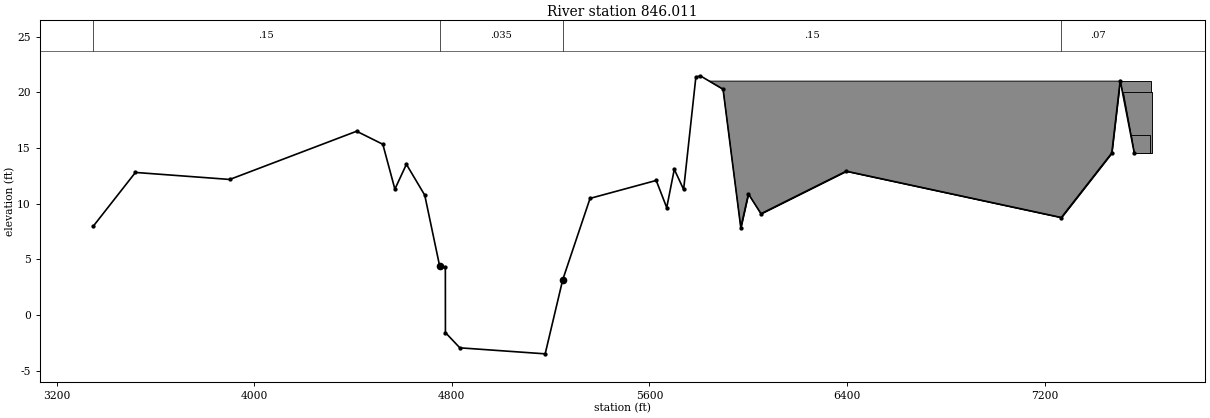
Type RM Length L Ch R = 1 ,846.011 ,442.15,846.01,315.96
XS GIS Cut Line= 6
     3211177.086    13764784.376     3210286.459     13763915.65
     3210175.245    13763801.309     3209756.269    13763566.751
     3209454.234    13763390.034     3207636.479     13762601.61
#Sta/Elev= 30
 3347.67    7.96 3519.17   12.81 3901.04   12.18 4414.63   16.51  4520.7   15.34
 4569.54   11.31 4616.17   13.54 4690.42   10.77 4751.02    4.38 4773.85    4.29
 4774.11   -1.57 4832.45   -2.94    5178   -3.48 5248.98    3.17 5359.65   10.48
 5627.49   12.09 5670.07    9.65 5700.68   13.09 5738.49   11.28 5787.96   21.36
 5805.68   21.49 5898.14   20.28 5969.98    7.84 6000.78   10.88 6051.79     9.1
 6396.93   12.92 7267.74    8.76 7471.88   14.55 7506.09   21.06  7562.8   14.57
#Mann= 4 ,-1 , 0
 3347.67     .15       0 4751.02    .035       0 5248.98     .15       0
 7267.74     .07       0
#Block Obstruct= 4 ,-1
 5820.59 7509.08   20.25 5838.23 7631.08   21.01 7511.32 7636.47   19.99
 7523.24 7624.55   16.19
Bank Sta=4751.02,5248.98
XS Rating Curve= 0
Exp/Cntr=.3,.1

Chan Stop Cuts=-1

--- A107_00_00.g02 (geometry) ---

Geom Title=A107-00-00 June 2007 (Floodway)
Version=Version 3.0.1  Mar 2001

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
River Reach=A107-00-00       ,A107-00-00_0008